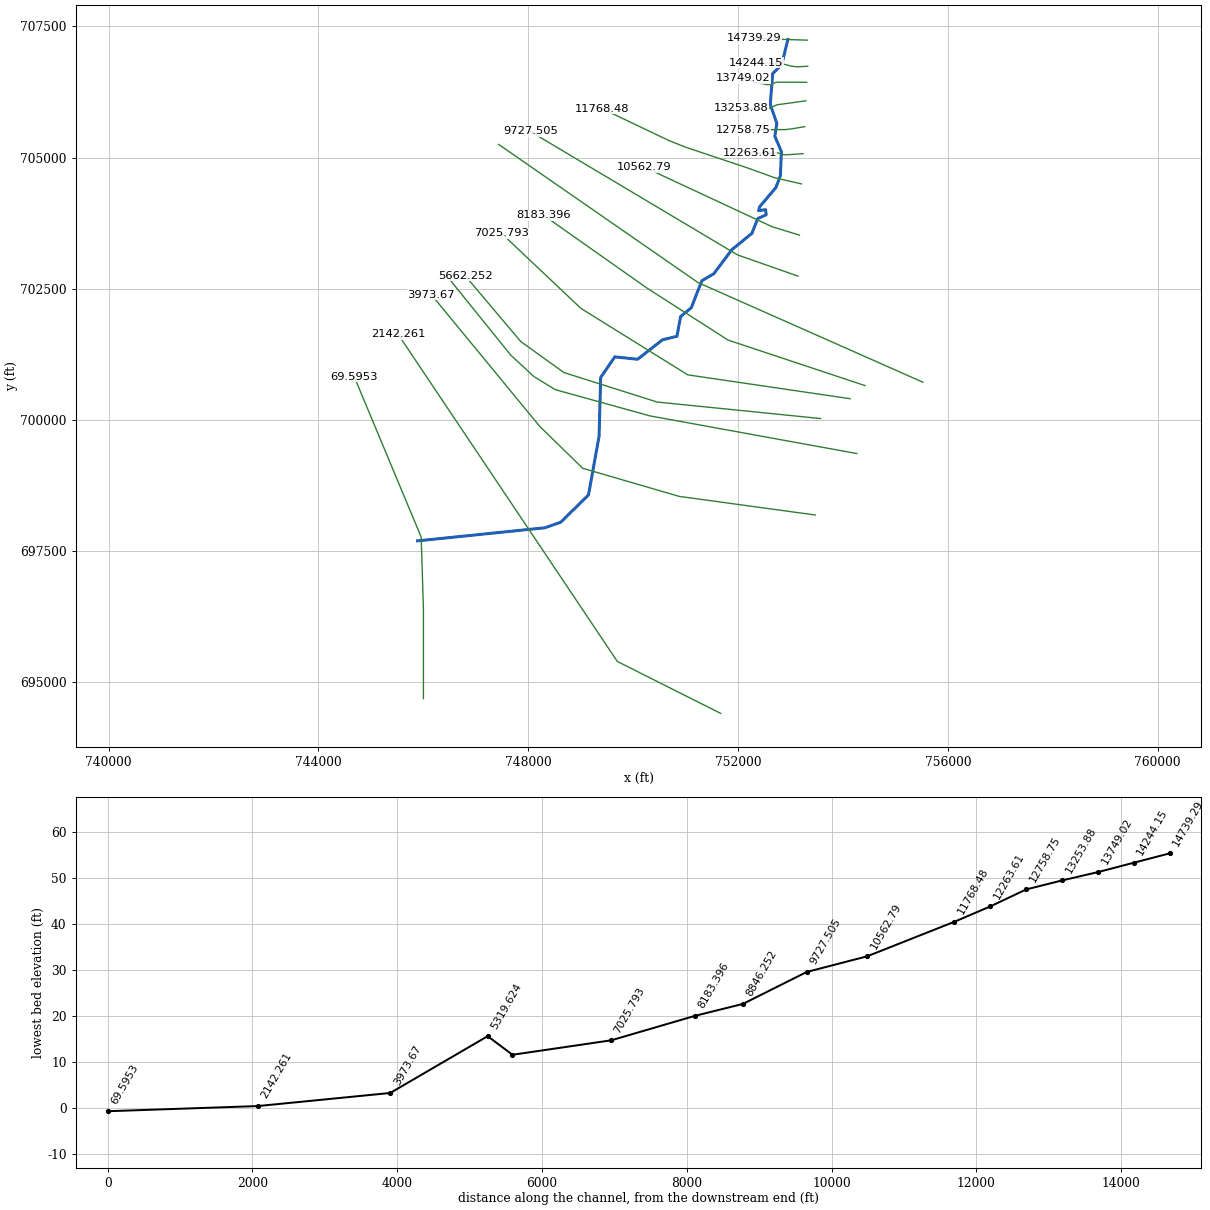
--- 6117_ras.prj (project) ---

Proj Title=6117
Current Plan=p01
Default Exp/Contr=0.3,0.1
English Units
Geom File=g01
Flow File=f01
Plan File=p01
Y Axis Title=Elevation
X Axis Title(PF)=Main Channel Distance
X Axis Title(XS)=Station
BEGIN DESCRIPTION:
RFD model 6117 exported to HEC-RAS
END DESCRIPTION:

--- 6117_ras.p01 (plan) ---

Plan Title=Plan 01
Program Version=4.10
Short Identifier=Plan 01
Geom File=g01
Flow File=f01
Subcritical Flow
Calc Critical at every XS
Secant Critical Depth

--- 6117_ras.f01 (steady flow) ---

Flow Title=Flow 01
Program Version=5.01
Number of Profiles= 6
Profile Names=10yr,25yr,50yr,100yr,100plus,500yr
River Rch & RM=6117,17,14739.29
 1214.47 2248.46 3344.69 4508.05 6581.75 9997.91
River Rch & RM=6117,17,14244.15
 1384.45 2579.62 3853.82 5213.68 7611.98 11421.1
River Rch & RM=6117,17,13749.02
 1388.47 2587.57 3866.14 5230.88 7637.0911456.03
River Rch & RM=6117,17,13253.88
 1397.43 2605.38 3893.86 5269.72 7693.7911535.44
River Rch & RM=6117,17,12758.75
 1405.62 2621.73 3919.36  5305.5 7746.0411608.85
River Rch & RM=6117,17,12263.61
 1431.84 2674.43 4001.93 5421.83 7915.8711849.06
River Rch & RM=6117,17,11768.48
 1436.36  2683.5 4016.14 5441.82 7945.0511890.18
River Rch & RM=6117,17,10562.79
 1616.54  3048.7 4591.32 6255.83 9133.5113568.05
River Rch & RM=6117,17,9727.505
 1679.68 3177.19 4794.28  6543.8 9553.9514157.41
River Rch & RM=6117,17,8846.252
 1712.94 3246.14 4904.38 6701.47 9784.1414485.21
River Rch & RM=6117,17,8183.396
 1717.33 3255.25 4918.93 6722.31 9814.5814528.52
River Rch & RM=6117,17,7025.793
 1723.47 3268.08  4939.5 6751.87 9857.7314590.31
River Rch & RM=6117,17,5662.252
 1759.12 3342.83 5059.65 6924.8710110.3114952.76
River Rch & RM=6117,17,5319.624
 1762.62 3350.19 5071.48 6941.9310135.2214988.56
River Rch & RM=6117,17, 3973.67
  1813.3 3456.71 5242.98 7189.2410496.2915506.02
River Rch & RM=6117,17,2142.261
 1867.24 3570.38  5426.3 7454.0210882.8716059.26
River Rch & RM=6117,17, 69.5953
 2464.79 4802.96 7392.1510268.0614991.3621669.56
Boundary for River Rch & Prof#=6117,17,1
Up Type= 0
Dn Type= 2
Boundary for River Rch & Prof#=6117,17,2
Up Type= 0
Dn Type= 2
Boundary for River Rch & Prof#=6117,17,2
Up Type= 0
Dn Type= 2
Boundary for River Rch & Prof#=6117,17,2
Up Type= 0
Dn Type= 2
Boundary for River Rch & Prof#=6117,17,2
Up Type= 0
Dn Type= 2
Boundary for River Rch & Prof#=6117,17,2
Up Type= 0
Dn Type= 2

--- 6117_ras.g01 (geometry) ---

Geom Title=6117
Program Version=4.10

River Reach=6117,17
Reach XY= 30
752950.860799849707250.415823057752831.893989325706769.304373503
752660.539822698706601.075206831752614.706489384706014.616873533
752739.706489384705650.033540174752701.685656041705407.846040174
752826.685656041705110.971040174752807.935656041704653.679373547
752722.518989325704428.679373503752410.539822698704059.408540174
752392.310656041703987.012706846752525.643989325704005.762706861
752537.102322698703908.887706846752374.602322668703835.971040159
752266.268989354703556.283540159751881.373156071703242.221040174
751538.143989384702785.450206846751310.018989414702650.554373533
751107.935656041702135.450206846750904.810656041701968.262706831
750835.018989325701592.221040189750561.060656011701525.554373518
750084.498156041701153.679373503749650.643989384701199.512706846
749381.199544936700807.672429055749349.949544936699682.672429055
749148.734074712698568.133992717748619.387119561698046.349136963
748316.903145254697940.479745939745889.469251007697690.930467084

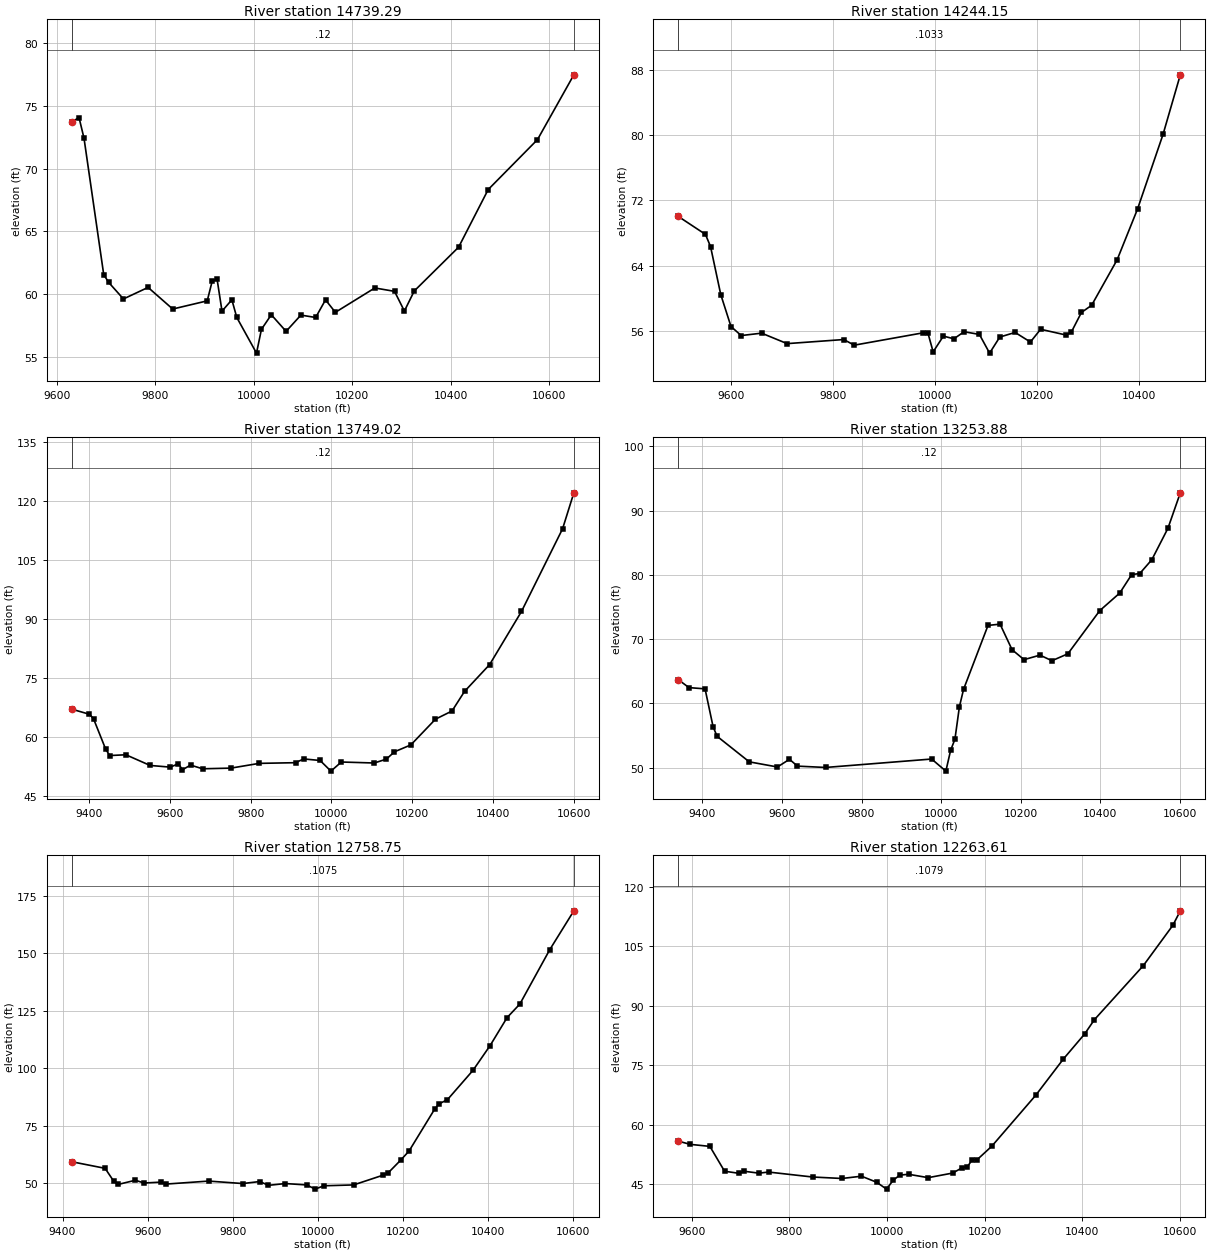
Type RM Length L Ch R = 1 ,14739.29,495.134600,495.134600,495.134600
XS GIS Cut Line= 4
753319.845242113  707238.6667974  752951.7529746707249.318542659
752949.763519436707249.523648351752301.223884493707272.963812798
#Sta/Elev= 30
9630.75473.756669645.605 74.05189655.60972.426239695.62661.56439 9705.6360.94339
9735.64359.624849785.66460.544279835.68558.822099905.714 59.47329915.71861.02858
9925.72261.204479935.72658.654019955.73559.558649965.73958.1496510005.7755.30943
10015.7757.2048110035.7958.3659410065.81 57.044310095.8358.3377410125.8458.14941
10145.8659.5525210165.8758.5593810245.9260.4995710285.9560.2306810305.9658.66184
10325.9860.2588910416.0363.7495810476.0768.3375310576.1472.3170110649.9677.47647
#Mann= 3 , 0 , 0
9630.754    0.12       09630.754    0.12       010649.96    0.12       0
#XS Ineff= 2 , 0
       0                               0
Bank Sta=9630.754,10649.96
Exp/Cntr=0.3,0.1

Type RM Length L Ch R = 1 ,14244.15,495.134600,495.134600,495.134600
XS GIS Cut Line= 6
753327.793577433706741.892038405753135.951625794706728.942814752
 753019.44392097706741.709953994752869.227311254706782.234681115
752798.323351085706792.246692345752351.127274394706808.571265385
#Sta/Elev= 30
 9497.0270.033789550.36567.832779560.39166.338749580.44460.455249600.49756.54145
 9620.5555.43434 9660.5655.727399710.60954.444979821.72554.945949842.25654.25543
9976.96755.763639987.05655.694569997.06653.4353110017.16 55.367310037.7655.03646
10057.7855.90207 10087.855.5733310107.8153.2807910127.8255.2507610157.8455.81609
10187.8654.6419110207.88 56.203310257.9155.4964410267.9255.8296210287.9358.26162
10307.9459.1410810357.9764.71342   1039870.9331910448.0380.0778110481.9387.37867
#Mann= 3 , 0 , 0
 9497.02  0.1033       0 9497.02  0.1033       010481.93  0.1033       0
#XS Ineff= 2 , 0
       09518.801                       0
Bank Sta=9497.02,10481.93
Exp/Cntr=0.3,0.1

Type RM Length L Ch R = 1 ,13749.02,495.134700,495.134700,495.134700
XS GIS Cut Line= 6
753308.788988829706435.103680387752724.766402811706436.778242514
752646.514207035706394.055059448752562.375890166706390.067261115
752347.603741854706429.337965012752098.983260095706515.269861847
#Sta/Elev= 30
9356.98267.016779400.86965.714679410.89264.568469440.95956.834159450.98255.21188
9491.07155.407089551.11652.689499601.12552.259669621.13153.129769631.133 51.5909
9651.13952.77956 9681.15 51.84039751.24352.011329821.33753.219089911.41853.39206
9931.41954.349139972.14153.954299998.917 51.2447 10024.8 53.5662 10106.253.31153
10136.2954.3016610156.39 56.167410196.8557.9154210257.9164.4688410298.8966.55056
10329.8171.5237710392.1378.37633   1047191.8917610572.78 112.93510600.67122.0858
#Mann= 3 , 0 , 0
9356.982    0.12       09356.982    0.12       010600.67    0.12       0
#XS Ineff= 2 , 0
       0 9372.67                       0
Bank Sta=9356.982,10600.67
Exp/Cntr=0.3,0.1

Type RM Length L Ch R = 1 ,13253.88,495.134600,495.134600,495.134600
XS GIS Cut Line= 6
753291.708895624706081.044868007752742.539209962706005.725841492
 752596.43938452  705941.5142335 752495.92038095705922.758630112
752280.638753355705919.712142006752054.255093485705947.000455782
#Sta/Elev= 30
9339.58663.688479366.56362.441939406.96662.249279427.16756.341779437.26754.85803
9518.07150.884349588.76850.085519619.00251.281459639.15850.217379709.70350.01098
9976.15251.3238110011.8849.4401110023.8552.6887710034.65  54.405 10045.9 59.4596
 10056.362.1684810117.7772.1262410148.0472.3218710178.1968.3423610208.2766.79688
10248.2967.49828 10278.366.6288610318.3267.7044810398.4374.4229110448.6377.16234
10478.7580.0504710498.9180.1969810529.26 82.354810569.7287.2464710600.8292.76759
#Mann= 3 , 0 , 0
9339.586    0.12       09339.586    0.12       010600.82    0.12       0
#XS Ineff= 2 , 0
       09353.585                       0
Bank Sta=9339.586,10600.82
Exp/Cntr=0.3,0.1

Type RM Length L Ch R = 1 ,12758.75,495.134600,495.134600,495.134600
XS GIS Cut Line= 6
753272.183346659705589.478224456753046.578199178  705550.5622648
752892.833156675705531.958209932752697.546152532705533.673903316
752326.957177043705513.511415824752098.505614936705523.944264516
#Sta/Elev= 30
9421.75759.39531 9500.0856.527859520.376  50.9069530.52349.519699571.11451.35229
9591.40950.14157    963250.536769642.14849.672519743.124  50.984 9823.4449.91605
9863.46350.79301 9883.4849.135689923.514 49.91089973.544 49.30459993.54547.48806
10013.5748.9412310083.7149.3158810153.8553.6165210163.8754.3655810193.9360.02524
10213.9764.0703210274.0682.2772910284.0784.5267610304.0886.3862510364.1299.14314
10404.13109.863110444.13122.066810474.14127.960810544.29151.575610600.96168.4973
#Mann= 3 , 0 , 0
9421.757  0.1075       09421.757  0.1075       010600.96  0.1075       0
#XS Ineff= 2 , 0
       09437.519                       0
Bank Sta=9421.757,10600.96
Exp/Cntr=0.3,0.1

Type RM Length L Ch R = 1 ,12263.61,495.134600,495.134600,495.134600
XS GIS Cut Line= 6
 753239.62096855705073.032069206752911.675038308705051.928885356
752847.324358493705057.240092337752753.160152525705089.575486973
752458.559576601705076.607305676752219.859949321705095.939512879
#Sta/Elev= 30
9572.199 55.91019596.89855.095449637.02554.58693 9667.1248.319129697.21547.78567
9707.24748.313199737.34247.836719757.40548.110349847.56446.860349907.58146.49227
9947.68547.06444 9978.5545.55292    999943.8061710012.5846.0462810026.1447.34051
 10044.247.5495810084.3846.6975110134.4347.8586110154.4749.23086 10164.5 49.4252
10174.5251.2117910184.5451.2231210214.62 54.625310304.7667.4924110361.2176.60774
10404.7982.92128 10424.886.52922 10525.1100.176510585.62110.3416 10600.9113.9952
#Mann= 3 , 0 , 0
9572.199  0.1079       09572.199  0.1079       0 10600.9  0.1079       0
#XS Ineff= 2 , 0
       09577.326                       0
Bank Sta=9572.199,10600.9
Exp/Cntr=0.3,0.1

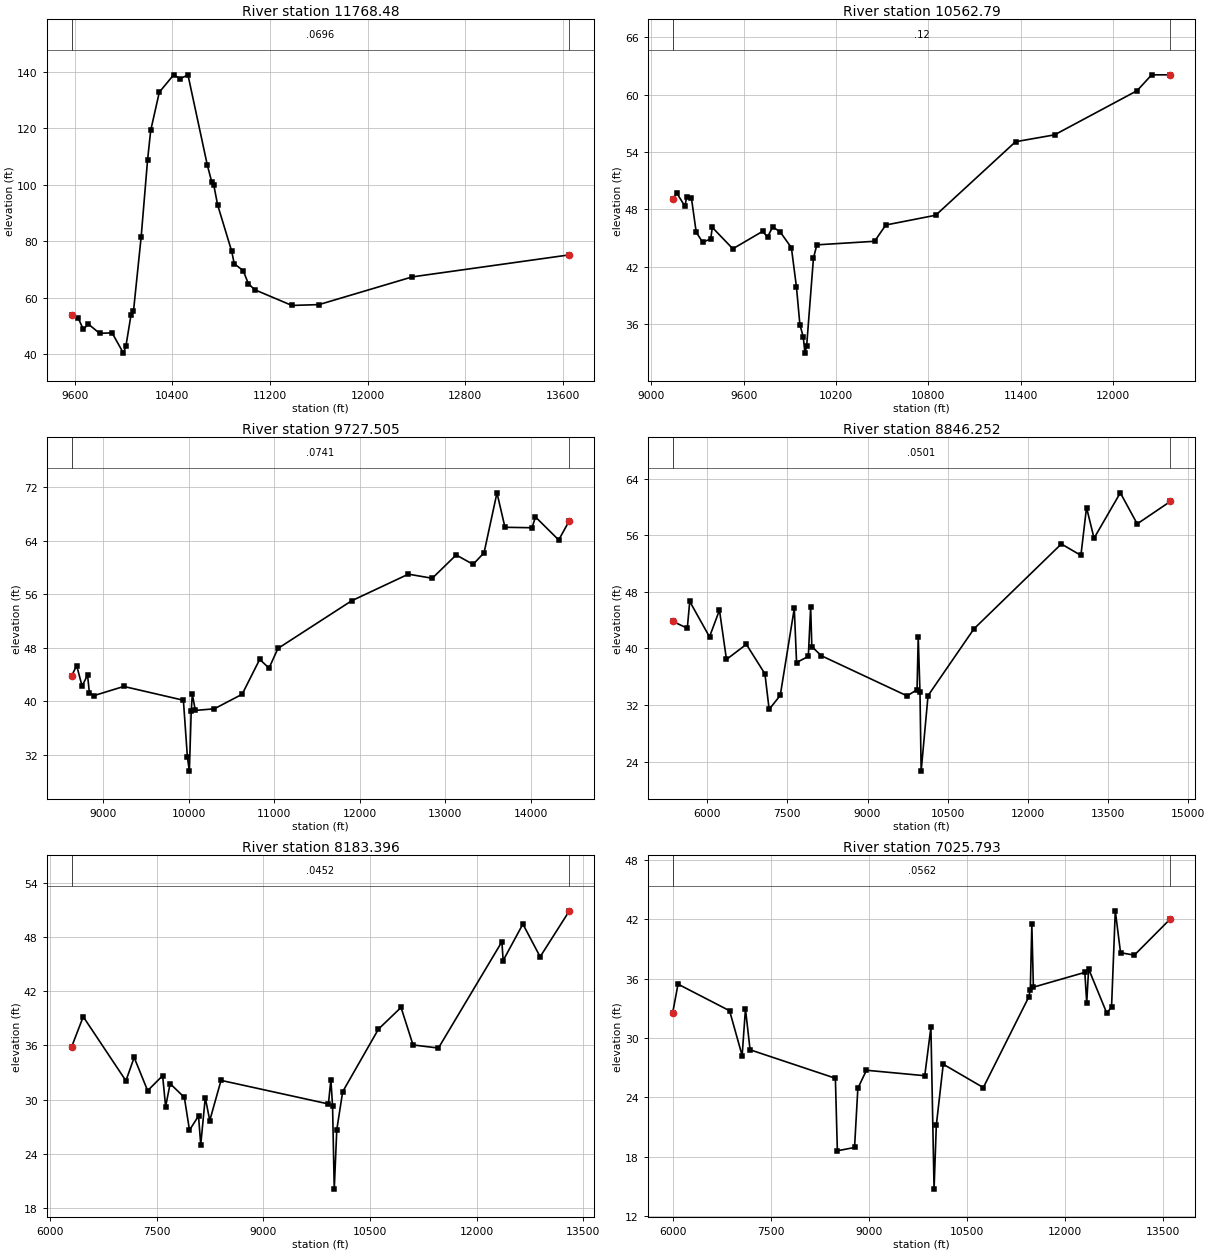
Type RM Length L Ch R = 1 ,11768.48,1205.684000,1205.684000,1205.684000
XS GIS Cut Line= 6
753209.358355183704496.926209388752708.605305523704612.136158437
752195.738681287704796.878271937750986.349659115705202.168227151
750665.675141603705331.510322526749403.811618328 705934.51544486
#Sta/Elev= 30
 9573.9754.039859629.538 52.76619670.42848.87935 9711.3850.77182 9803.7147.48097
  9906.347.65461 9998.6340.4793810019.1642.9145310060.5553.8198610081.2555.27864
10144.3181.6255610196.97108.917110222.51119.280710293.03132.818710410.59138.9635
10464.03137.5865 10527.8138.934710686.46107.006610723.43100.911610739.07100.0322
10770.6492.9671210886.1676.5163610907.1372.1052910980.5269.6558911022.4665.07752
11074.8862.9128711379.49 57.355411601.2357.6490612366.1567.4632213653.1175.25374
#Mann= 3 , 0 , 0
 9573.97  0.0696       0 9573.97  0.0696       013653.11  0.0696       0
#XS Ineff= 2 , 0
       0                               0
Bank Sta=9573.97,13653.11
Exp/Cntr=0.3,0.1

Type RM Length L Ch R = 1 ,10562.79,835.290000,835.290000,835.290000
XS GIS Cut Line= 3
753171.406127929703520.847353394752651.660495907703679.517252798
750212.424384773704816.670030628
#Sta/Elev= 30
9139.09449.118239166.70349.695089218.98148.323469229.43749.259849260.80449.22315
9292.17145.617189333.993 44.57169386.27144.912059396.72746.122929530.05343.88544
9722.96845.702649756.06845.123769789.168 46.18189837.49745.650889910.53444.00737
9943.63439.876189965.70135.967739987.76734.661939998.80132.9761810009.8333.75126
10053.9742.9123210076.0344.2982610451.1744.6697310523.8346.3721410848.3647.39451
11366.9355.0792811620.6955.7994312156.8560.4168912251.5162.07562 12373.862.07457
#Mann= 3 , 0 , 0
9139.094    0.12       09139.094    0.12       0 12373.8    0.12       0
#XS Ineff= 2 , 0
       09470.292                       0
Bank Sta=9139.094,12373.8
Exp/Cntr=0.3,0.1

Type RM Length L Ch R = 1 ,9727.505,881.252600,881.252600,881.252600
XS GIS Cut Line= 3
753141.434848245702739.482073923751989.213526279 703144.00083968
748037.824637413705498.167506352
#Sta/Elev= 30
8631.17543.797418690.98745.330578754.57742.263828818.167 43.93668839.36441.30126
8892.35640.849359242.10242.223889938.72940.16347 9985.2931.7232610008.5729.57648
10030.1338.5093610043.4941.0459510078.4138.6429810299.5838.87965 10625.541.05418
10831.1846.2712610939.79 44.956911044.5547.8987311905.9355.0151412569.4358.99099
12848.7958.3786413128.1661.8597613326.0460.4542413454.0962.1802913605.4171.13743
13698.5365.9913714015.8465.9214614054.9267.5403214327.1164.0974114451.8666.98552
#Mann= 3 , 0 , 0
8631.175  0.0741       08631.175  0.0741       014451.86  0.0741       0
#XS Ineff= 2 , 0
       09254.957                       0
Bank Sta=8631.175,14451.86
Exp/Cntr=0.3,0.1

Type RM Length L Ch R = 1 ,8846.252,662.856200,662.856200,662.856200
XS GIS Cut Line= 3
755525.571339124700715.559130091751236.743105471702616.289824545
747436.743105501705249.623157874
#Sta/Elev= 30
5353.98143.833595628.05742.850325673.45146.644056043.70441.63134 6229.6545.41483
6360.90738.439846732.801 40.57527080.25336.404337159.38531.380137367.20833.35274
7629.72145.65334 7672.5937.999537892.23538.873997935.98745.823117957.86340.26767
8132.87238.976369740.76633.281789926.71234.162869948.58941.624029981.40333.86407
10003.2822.6415110132.4133.3223610990.9242.7649212626.5354.7759112992.3853.16069
13097.7259.9308713238.1755.5843413729.7662.0071814045.7857.6167714668.3760.80212
#Mann= 3 , 0 , 0
5353.981  0.0501       05353.981  0.0501       014668.37  0.0501       0
#XS Ineff= 2 , 0
       0 9360.44                       0
Bank Sta=5353.981,14668.37
Exp/Cntr=0.3,0.1

Type RM Length L Ch R = 1 ,8183.396,1157.602500,1157.602500,1157.602500
XS GIS Cut Line= 4
754420.729223311700651.600542963751809.618112147 701519.65609853
750261.007001072702512.711654067748288.784778863703901.600542977
#Sta/Elev= 30
6301.72535.826816465.83539.194027066.508 32.07837182.42734.671127372.11330.98182
7582.87632.645677625.02829.204767688.25731.761517888.48230.237287960.83326.60002
8087.62728.171858119.32624.990918182.72330.203958246.12127.666648404.61432.12461
9915.40929.50644 9949.7932.199859973.54929.291579997.30820.0494910032.9526.64301
 10116.130.8685110619.3737.8187810937.0540.22244 11105.436.0594511462.9735.71398
12355.8347.5180112373.2445.4281812651.1349.4791812893.9845.84642 13305.250.94966
#Mann= 3 , 0 , 0
6301.725  0.0452       06301.725  0.0452       0 13305.2  0.0452       0
#XS Ineff= 2 , 0
       09366.174                       0
Bank Sta=6301.725,13305.2
Exp/Cntr=0.3,0.1

Type RM Length L Ch R = 1 ,7025.793,1363.540900,1363.540900,1363.540900
XS GIS Cut Line= 4
754136.007001042700401.600542992751040.882105201 700856.59696649
749004.062556595702123.822765201747490.173667729703554.378320739
#Sta/Elev= 30
6001.61832.538556083.49535.453966871.87832.76395 7063.9228.228777114.45832.94493
 7185.2128.818088489.07425.942628519.397 18.61198782.19118.946428832.72824.92777
8964.12526.750469855.35926.199199949.57831.077179997.76214.7369110032.02 21.1825
10138.0227.3605510750.4424.9986911445.3134.1522911468.8734.8908711492.4241.48373
11515.9835.1460512302.2536.6397912331.3733.5756812360.4936.9924812637.1232.53857
12710.7933.1215712768.1642.8622412848.3838.6276613059.3638.3856813611.7342.05767
#Mann= 3 , 0 , 0
6001.618  0.0562       06001.618  0.0562       013611.73  0.0562       0
#XS Ineff= 2 , 0
       09398.195        10437.13       0
Bank Sta=6001.618,13611.73
Exp/Cntr=0.3,0.1

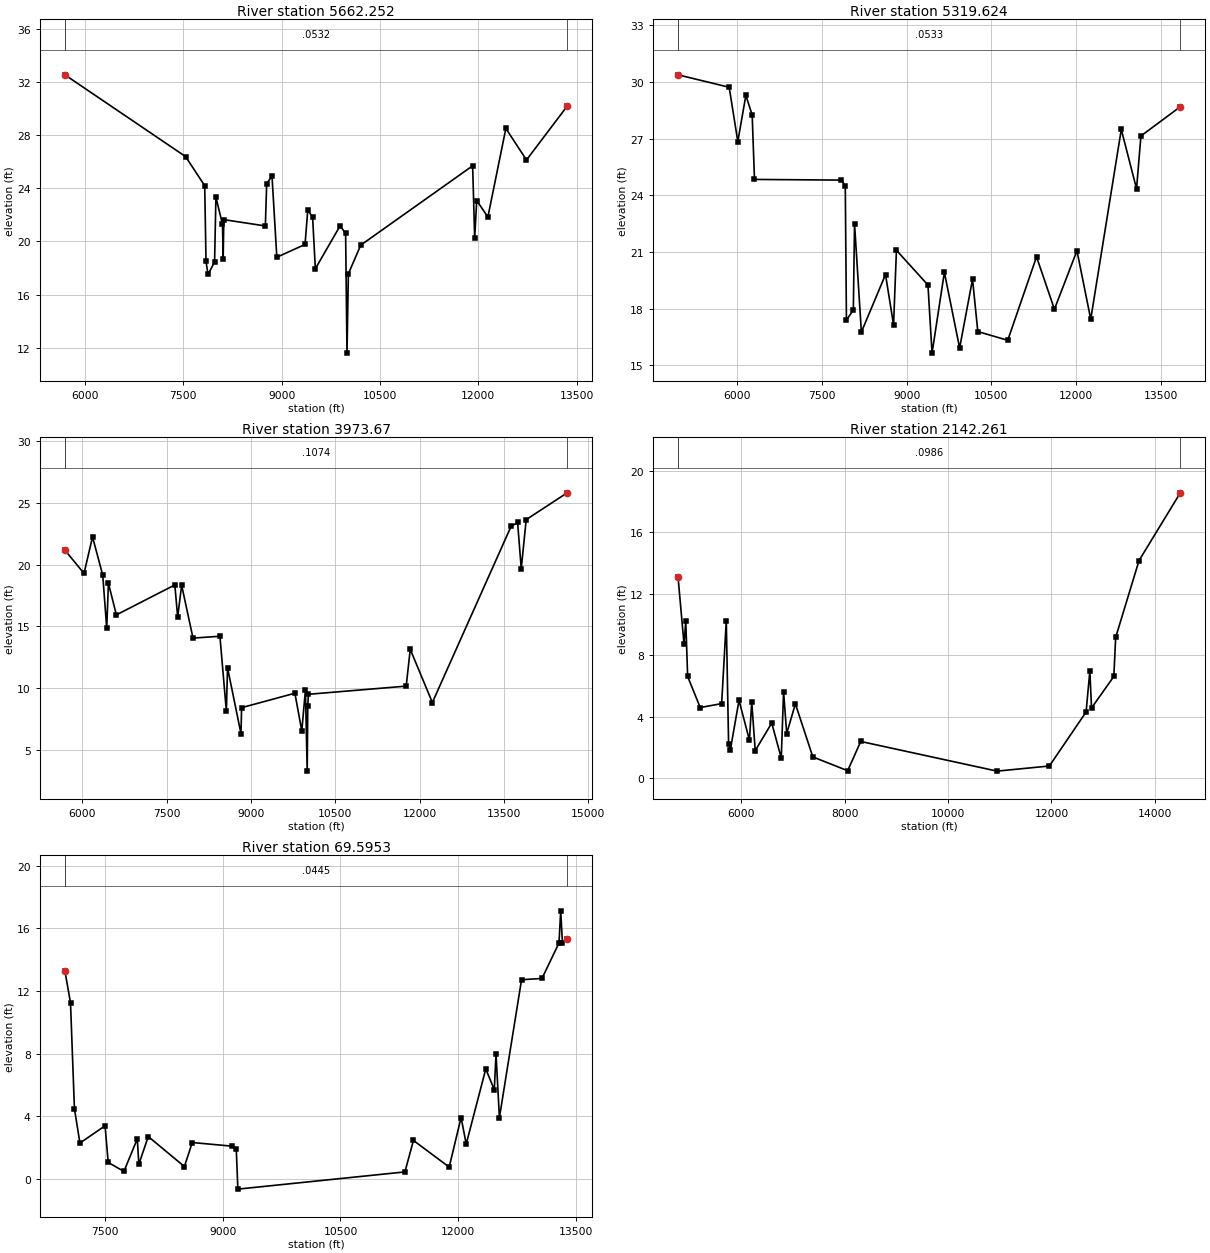
Type RM Length L Ch R = 1 ,5662.252,342.628300,342.628300,342.628300
XS GIS Cut Line= 5
753575.430502445700023.181319535750455.383323163700338.523995757
748678.981501251700900.743294522747857.239611775701491.454605415
746795.234697491702749.003281668
#Sta/Elev= 30
5696.61132.540427536.36726.390037827.84424.198797847.946 18.51867878.09917.51584
7978.60818.46564 7998.7123.32985 8099.2221.292228109.27118.677658119.32121.64353
8752.53121.168398772.633 24.34978853.93324.926328927.35518.81534  9357.419.77719
9399.35522.359499472.77821.833819514.73317.948899892.33321.178489976.24420.61128
9997.22211.59878 10018.217.56732   1020719.7254511912.7925.6956511943.7820.23855
11974.7823.0799112145.2721.8421112419.27 28.5073 12733.426.1327413353.8230.18046
#Mann= 3 , 0 , 0
5696.611  0.0532       05696.611  0.0532       013353.82  0.0532       0
#XS Ineff= 2 , 0
       08828.116        10389.24       0
Bank Sta=5696.611,13353.82
Exp/Cntr=0.3,0.1

Type RM Length L Ch R = 1 ,5319.624,1345.954400,1345.954400,1345.954400
XS GIS Cut Line= 6
754264.914626986699355.981690243750319.269783199700074.242280737
748515.286092609700574.047285929748108.939774394700823.021469042
747667.218558252701231.804688856 746459.81621021702727.018061653
#Sta/Elev= 30
4957.83430.374375862.373 29.71556014.83826.840386157.13929.285186268.94728.24883
6309.60424.835387844.41924.80056 7915.5724.494877935.89917.381998057.87117.92592
8079.17422.494958200.171 16.75278627.07419.800298769.37417.132838820.19621.08419
9377.443 19.2483 9450.0815.638389667.99119.918719937.78615.9092910166.0719.55113
10259.4616.7800610788.68 16.317611297.9820.7382611614.1917.9628212012.7521.06128
12256.4617.43511 12796.827.4806213066.72 24.337713143.84 27.136413840.5128.68425
#Mann= 3 , 0 , 0
4957.834  0.0533       04957.834  0.0533       013840.51  0.0533       0
#XS Ineff= 2 , 0
       0 8899.22        10366.48       0
Bank Sta=4957.834,13840.51
Exp/Cntr=0.3,0.1

Type RM Length L Ch R = 1 , 3973.67,1831.408900,1831.408900,1831.408900
XS GIS Cut Line= 5
753471.720404953698184.288458064750880.059997827698538.617029354
749037.551427096699075.171723038748217.533876389699874.941926792
746152.304489493702385.612946242
#Sta/Elev= 30
5690.63421.164056030.487 19.28436181.88222.233616363.55619.140776434.20814.85353
6464.48718.488296605.78915.932667645.37118.355187695.83615.747737766.48718.33292
7968.34814.056958447.07414.206258561.6438.1548618582.474 11.66478822.0286.323058
8832.4438.4344659780.2439.6027229902.9396.561438 9967.729.8474599998.9663.307112
10009.388.580717 10019.8 9.5158411759.43 10.176411831.3913.1488512224.928.851788
13624.0223.0817213740.5523.3998513805.29 19.6702 13893.523.6321714621.84 25.7964
#Mann= 3 , 0 , 0
5690.634  0.1074       05690.634  0.1074       014621.84  0.1074       0
#XS Ineff= 2 , 0
       0 9084.22        10420.91       0
Bank Sta=5690.634,14621.84
Exp/Cntr=0.3,0.1

Type RM Length L Ch R = 1 ,2142.261,2072.665500,2072.665500,2072.665500
XS GIS Cut Line= 3
751668.415565073694401.617566437749699.014523417 695391.20089978
745519.327023447701628.180066451
#Sta/Elev= 30
4780.10613.091914895.8438.7158044929.41810.21868 4965.826.6205375209.2044.600944
5623.2884.8563315712.81910.244835757.5852.2443425791.1591.8414655959.0315.071743
6160.4772.4771586205.2434.9607946272.3921.7971396591.7093.5943636776.007 1.31441
6820.7735.6249626881.2512.9113157048.9144.8431377386.5491.3896178060.0930.492229
8312.8872.39498110949.170.46538311960.350.79884512670.594.31379312742.816.975882
12775.454.57211113206.566.62273713242.499.163186 13693.814.1597814492.13 18.5667
#Mann= 3 , 0 , 0
4780.106  0.0986       04780.106  0.0986       014492.13  0.0986       0
#XS Ineff= 2 , 0
       08178.218        11462.37       0
Bank Sta=4780.106,14492.13
Exp/Cntr=0.3,0.1

Type RM Length L Ch R = 1 , 69.5953,0.000000,0.000000,0.000000
XS GIS Cut Line= 4
 746001.09785679694683.735622004 746001.09785679696402.485621989
745957.695078999697765.332844228744681.653412342 700820.88839978
#Sta/Elev= 30
6992.15213.285767063.41611.255077113.4164.4846517183.4162.2872997503.4163.391226
7543.4161.0488217743.4160.4763337913.4162.5558657933.4160.9353478053.416  2.7042
8513.4160.7863478613.4162.3224659123.6252.0873879173.6511.9111749193.661-0.65617
11320.330.444064 11428.72.45465611883.850.75299512035.57 3.9207112100.592.224832
12349.847.02673912458.215.69071112479.897.99057212523.243.911564   1280512.72541
13065.0912.8070213281.8315.07527 13303.517.1282313325.1715.1028913385.7415.35708
#Mann= 3 , 0 , 0
6992.152  0.0445       06992.152  0.0445       013385.74  0.0445       0
#XS Ineff= 2 , 0
       09053.162        11519.51       0
Bank Sta=6992.152,13385.74
Exp/Cntr=0.3,0.1